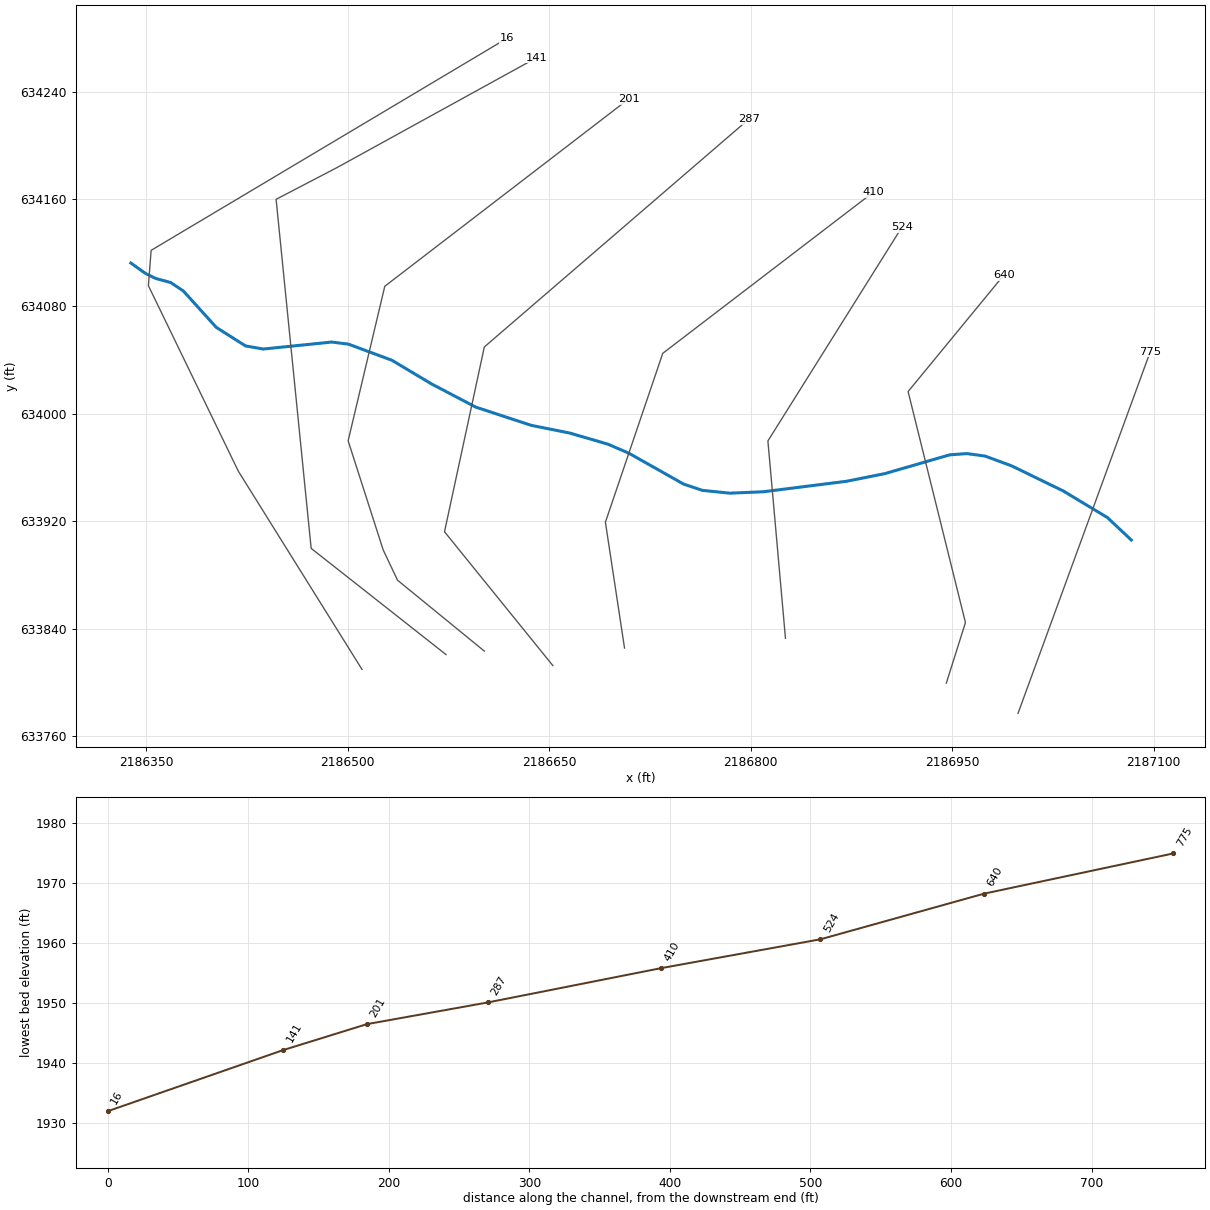
--- CRISLPRN.prj (project) ---

Proj Title=CRISLPRN
Current Plan=p01
Default Exp/Contr=0,0
English Units
Geom File=g01
Flow File=f01
Plan File=p01
BEGIN DESCRIPTION:
----------MODEL BY WOOD PLC 2022----------
AFH study
Randolph County, WV
HEC-RAS Version: RAS 6.2
Vertical Datum: NAVD88
Projection: NAD 1983 StatePlane West Virginia S FIPS 4702 (US Feet)
Terrain: 1-meter LIDAR (FEMA Region III 3DEP collected 2016-2018)
Land Use: 2019 NLCD
Hydrologic Method:
WV SIR2010-5033 regression equations
Additional Model Notes:
None
END DESCRIPTION:
DSS Export Rating Curves= 0
DSS Export Rating Curve Sorted= 0
DSS Export Volume Flow Curves= 0
DXF OffsetX= 0
DXF OffsetY= 0
DXF ScaleX= 0
DXF ScaleY= 0

--- CRISLPRN.p01 (plan) ---

Plan Title=Floodplain
Program Version=6.20
Short Identifier=Floodplain
Geom File=g01
Flow File=f01
Subcritical Flow
K Sum by GR= 0
Std Step Tol= 0.01
Critical Tol= 0.01
Num of Std Step Trials= 20
Max Error Tol= 0.3
Flow Tol Ratio= 0.001
Split Flow NTrial= 30
Split Flow Tol= 0.02
Split Flow Ratio= 0.02
Log Output Level= 0
Friction Slope Method= 1
Unsteady Friction Slope Method= 2
Unsteady Bridges Friction Slope Method= 1
Parabolic Critical Depth
Global Vel Dist= 0 , 0 , 0
Global Log Level= 0
CheckData=True
Encroach Param=-1 ,0,0, 0
Mapping Interval=1HOUR
Computation Time Step Use Courant=        0
Computation Time Step Use Time Series=    0
Computation Time Step Count To Double=0
Computation Time Step Max Doubling=0
Computation Time Step Max Halving=0
Computation Time Step Residence Courant=0
Run HTab= 0
Run UNet= 0
Run Sediment= 0
Run PostProcess= 0
Run WQNet= 0
Run RASMapper=-1
UNET Theta= 0
UNET Theta Warmup= 0
UNET ZTol= 0
UNET ZSATol= 0
UNET MxIter= 0
UNET Max Iter WO Improvement= 0
UNET MaxInSteps= 0
UNET DtIC= 0
UNET DtMin= 0
UNET MaxCRTS= 0
UNET WFStab= 0
UNET SFStab= 0
UNET WFX= 1
UNET SFX= 1
UNET Gravity=32.174
UNET 1D Methodology=Finite Difference
UNET DSS MLevel= 1
UNET Pardiso=0
UNET DZMax Abort= 0
UNET Use Existing IB Tables= 0
UNET Froude Reduction=False
UNET Froude Limit= 0
UNET Froude Power= 0
UNET D1 Cores= 0
UNET WindReference=Eulerian
UNET WindDragFormulation=Hsu (1988)
UNET D2 Coriolis=0
UNET D2 Cores= 0
UNET D2 Theta= 1
UNET D2 Theta Warmup= 1
UNET D2 Z Tol= 0.01
UNET D2 Volume Tol= 0.01
UNET D2 Max Iterations= 20
UNET D2 Equation= 0
UNET D2 RampUpFraction=0.1
UNET D2 TimeSlices= 1
UNET D2 Turbulence Formulation=Non-Conservative (original)
UNET D2 Eddy Viscosity=0.3
UNET D2 Transverse Eddy Viscosity=0.1
UNET D2 Smagorinsky Mixing=0
UNET D2 BCVolumeCheck=0
UNET D2 Cores=0
UNET D2 SolverType=PARDISO (Direct)
UNET D2 Minimum Iterations= 2147483647
UNET D2 Maximum Iterations= 2147483647
UNET D2 Restart Number= 10
UNET D2 Relaxation Coeff=1.3
UNET D2 SOR Precondition Iterations= 10
UNET D2 ILUT Maximum Fill= 8
UNET D2 ILUT Tolerance=1E-08
UNET D1D2 MaxIter= 0
UNET D1D2 ZTol=0.01
UNET D1D2 QTol=0.1
UNET D1D2 MinQTol=1
Write IC File= 0
Write IC File at Fixed DateTime=0
Write IC File at Sim End=0
Echo Input=False
Echo Parameters=False
Echo Output=False
Write Detailed= 0
HDF Write Warmup=0
HDF Write Time Slices=0
HDF Flush=0
HDF Compression= 1
HDF Chunk Size= 1
HDF Spatial Parts= 1
HDF Use Max Rows=0
HDF Fixed Rows= 1
Calibration Method= 0
Calibration Iterations= 20
Calibration Max Change=0.05
Calibration Tolerance=0.2
Calibration Maximum=1.5
Calibration Minimum=0.5
Calibration Optimization Method= 1
WQ AD Non Conservative
WQ ULTIMATE=-1
WQ Max Comp Step=1HOUR
WQ Output Interval=15MIN
WQ Output Selected Increments= 0
WQ Output face flow=0
WQ Output face velocity=0
WQ Output face area=0
WQ Output face dispersion=0
WQ Output cell volume=0
WQ Output cell surface area=0
WQ Output cell continuity=0
WQ Output cumulative cell continuity=0
WQ Output face conc=0
WQ Output face dconc_dx=0
WQ Output face courant=0
WQ Output face peclet=0
WQ Output face adv mass=0
WQ Output face disp mass=0
WQ Output cell mass=0
WQ Output cell source sink temp=0
WQ Output nsm pathways=0
WQ Output nsm derived pathways=0
WQ Create Restart=0
WQ Fixed Restart=0
WQ System Summary=0
WQ Write To DSS=0
Sorting and Armoring Iterations= 10
XS Update Threshold= 0.02
Bed Roughness Predictor= 0
Hydraulics Update Threshold= 0.02
Energy Slope Method= 1
Volume Change Method= 1
Sediment Retention Method= 0
Sediment TS Multiplier= 1
Warm Up Method= 0
XS Weighting Method= 0
Number of US Weighted Cross Sections= 1
Number of DS Weighted Cross Sections= 1
Upstream XS Weight=0
Main XS Weight=1
Downstream XS Weight=0
Number of DS XS's Weighted with US Boundary= 1
Upstream Boundary Weight= 1
Weight of XSs Associated with US Boundary= 0
Number of US XS's Weighted with DS Boundary= 1
Downstream Boundary Weight= 0.5
Weight of XSs Associated with DS Boundary= 0.5
Percentile Method= 0
Sediment Output Level= 3
Mass or Volume Output= 0
Output Increment Type= 1
Profile and TS Output Increment= 1
Transport Output Increment 1
XS Output Flag= 0
XS Output Increment= 10
Read HDF5 Sediment Hotstart= 0
Sediment Hotstart Type= 0
Write Gradation File= 0
Read Gradation Hotstart= 0
Write HDF5 File= 1
Write Binary Output= 1
Write DSS Sediment File= 0
DSS Sediment Output Type= 1
SV Curve= 0
Specific Gage Flag= 0
Subcell Erosion Methods= 0
Subcell Deposition Methods= 0
Advection Scheme= 1
Matrix Solver= 0
Implicit Weighting Factor= 1
Maximum Outer Loop Convergence Iterations= 5
Convergence Maximum Absolute= 0.001
Convergence RMSE= 0.0001
Grain Fractions Max Abs Error= 0.001
Max Subgrid Regions= 1
Max Subgrid Length Scale= 3.402823E+38
Initial Layer Thickness= 3.402823E+38
Min Layer Thickness= 3.402823E+38
Max Layer Thickness= 3.402823E+38
Number of Layers= 5

--- CRISLPRN.f01 (steady flow) ---

Flow Title=Flow
Program Version=6.20
Number of Profiles= 1
Profile Names=P100yr
River Rch & RM=CRISLPRN,Main,775
     301
Boundary for River Rch & Prof#=CRISLPRN,Main            , 1
Up Type= 0
Dn Type= 3
Dn Slope=0.053479
DSS Import GetInterval= 0
DSS Import GetPeak= 0
DSS Import FillOption= 0

--- CRISLPRN.g01 (geometry) ---

Geom Title=Geometry
Program Version=6.20

River Reach=CRISLPRN        ,Main
Reach XY= 30
      2187083.45        633906.1     2187065.742      633922.767
     2187032.929      633942.559     2186994.387      633961.309
     2186974.596        633968.6     2186961.181      633970.451
     2186948.286      633969.544     2186900.117       633955.58
     2186871.471       633949.85     2186809.492      633942.038
     2186784.491      633940.996     2186764.179      633943.079
     2186750.117      633947.767     2186709.492      633970.684
     2186693.867      633977.455     2186665.221      633985.788
     2186636.575      633991.517     2186595.429      634005.058
     2186562.617      634022.246     2186532.929      634039.954
     2186500.637      634051.934     2186488.137      634053.496
2186437.16840115634048.2999680292186423.99523408634050.614173055
       2186402.2      634064.434     2186377.721      634091.517
     2186368.346      634097.767     2186356.885      634100.928
     2186349.482      634104.614     2186338.617      634112.357

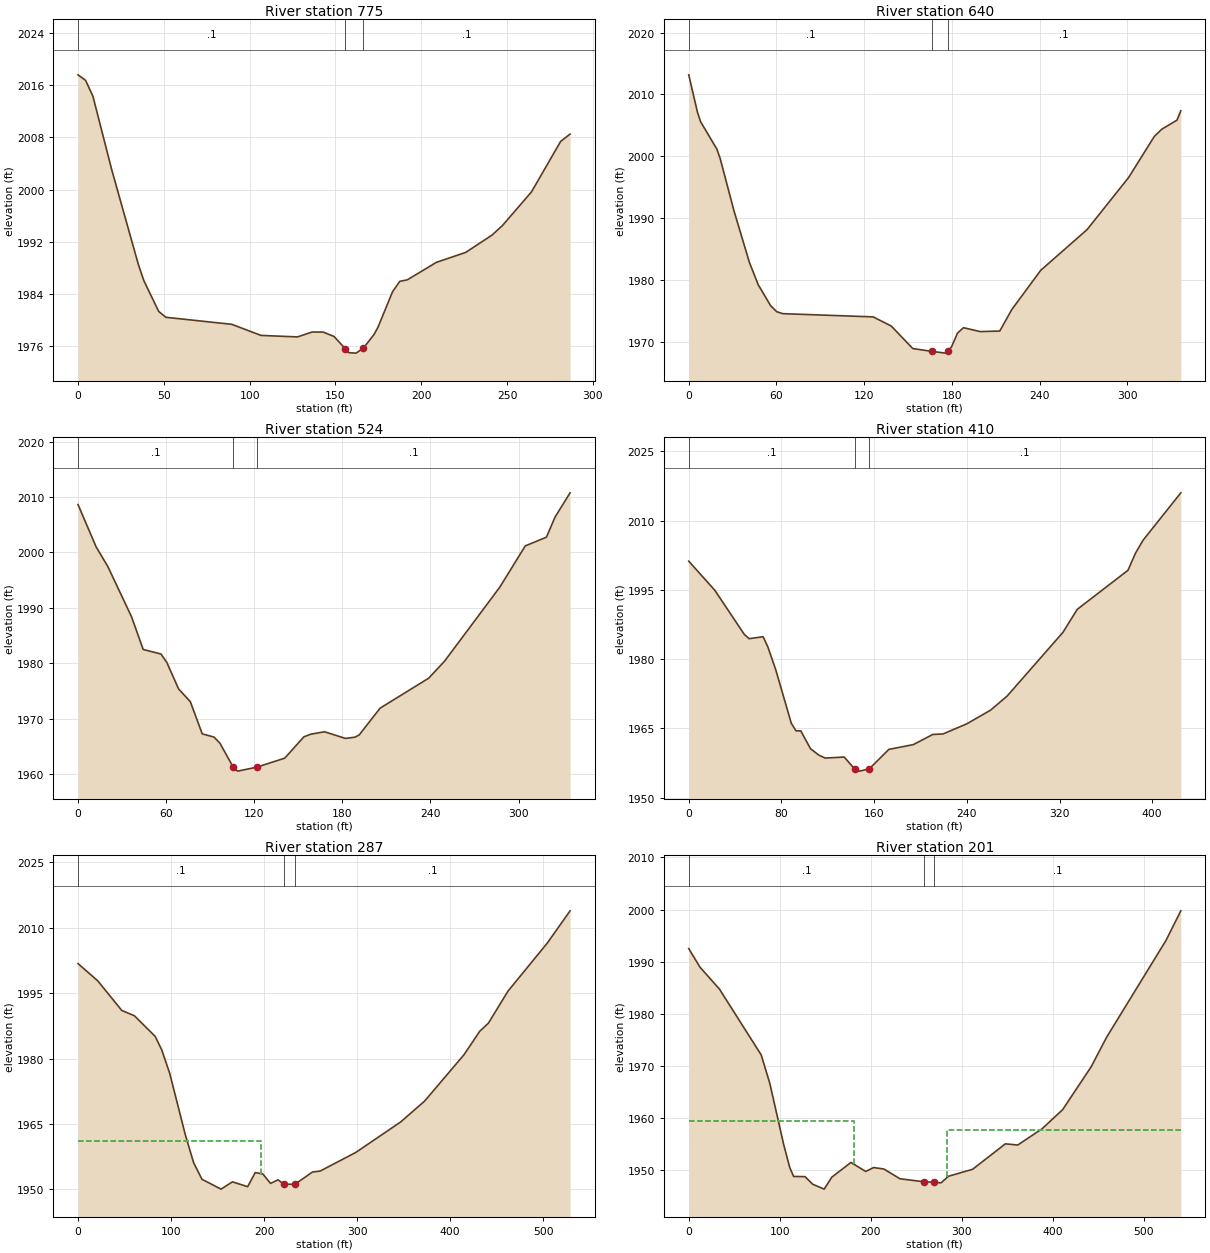
Type RM Length L Ch R = 1 ,775     ,131.7,134.7,137.9
XS GIS Cut Line= 2
2186999.10726678633777.0514391532187097.54722087634046.278783475
#Sta/Elev= 30
       0  2017.6     4.4 2016.76     8.7  2014.3    19.6 2003.08    35.2 1988.46
    38.4 1985.99      47 1981.29    51.2 1980.39    89.6 1979.31   106.6 1977.61
   127.9 1977.38   136.4 1978.13   142.9 1978.12   149.2 1977.44  155.681975.583
   157.7 1974.96     162 1974.89   166.2 1975.63   172.5 1977.76   174.8 1978.88
   183.3 1984.33   187.5 1985.91   191.8 1986.13   208.8 1988.82   225.9 1990.35
   241.1 1992.98   247.2 1994.44   264.2 1999.63   281.2 2007.38   286.7 2008.51
#Mann= 3 ,-1,0
       0      .1       0  155.68    .045       0   166.2      .1       0
Bank Sta=155.68,166.2
XS Rating Curve= 0 ,0
Exp/Cntr(USF)=0,0
Exp/Cntr=0.3,0.1

Type RM Length L Ch R = 1 ,640     ,117.1,116.4,115.2
XS GIS Cut Line= 4
2186945.73620733633799.5858864752186959.96848985633844.654781119
2186917.27164229634016.6281948932186988.43305489634103.207913552
#Sta/Elev= 30
       0 2013.17     5.9 2007.18     8.1 2005.59    19.2 2001.17    21.4 1999.71
      31 1991.13    41.5 1982.83    47.5 1979.24      56 1975.85    60.2 1974.87
    64.3 1974.56   126.1 1974.04   138.5 1972.56   153.2 1968.92   166.4 1968.46
   175.6 1968.18  176.961968.475   179.7  1969.2   183.8 1971.42   187.9 1972.29
   199.4 1971.66   212.7 1971.75   220.9 1975.22   240.7 1981.57   272.4 1988.15
   300.8 1996.57   318.4 2003.22   323.5 2004.38   333.9 2005.85   336.5 2007.35
#Mann= 3 ,-1,0
       0      .1       0   166.4    .045       0  176.96      .1       0
Bank Sta=166.4,176.96
XS Rating Curve= 0 ,0
Exp/Cntr(USF)=0,0
Exp/Cntr=0.3,0.1

Type RM Length L Ch R = 1 ,524     ,115.8,113.8,109.3
XS GIS Cut Line= 3
2186825.97424576633832.9437047522186812.90157048633979.861465052
2186912.52754812 634138.78861985
#Sta/Elev= 30
       0 2008.65    12.3 2001.03    20.3 1997.47    36.4 1988.44    44.4 1982.51
    56.5 1981.69    60.5 1980.16    68.5 1975.39    76.5 1973.09    84.6 1967.29
    92.6 1966.71    96.6 1965.63   105.6 1961.33   108.7 1960.57   121.7 1961.28
   140.8 1962.91   153.8 1966.75   158.5 1967.23   167.9 1967.67   182.1 1966.47
   188.6 1966.69   191.5  1967.1   205.7 1971.92   238.8 1977.33   249.5 1980.36
   287.2 1993.73   304.6 2001.19     319 2002.76   324.9  2006.4   335.1 2010.76
#Mann= 3 ,0,0
       0      .1       0   105.6    .045       0   121.7      .1       0
Bank Sta=105.6,121.7
XS Rating Curve= 0 ,0
Exp/Cntr(USF)=0,0
Exp/Cntr=0.3,0.1

Type RM Length L Ch R = 1 ,410     ,122,122.6,123.5
XS GIS Cut Line= 4
2186706.15945159633825.6784044272186691.92716907633919.374264345
2186734.62401663634045.0927599322186891.17912434634164.881137802
#Sta/Elev= 30
       0 2001.21    22.4 1994.95      48 1985.34    52.1 1984.43    64.2 1984.85
    68.3 1982.63    75.1 1977.69    88.5 1966.11    92.6 1964.46    96.7 1964.46
   105.1 1960.59   112.2 1959.22   117.8 1958.57   134.2 1958.79   143.1 1956.22
   147.4 1955.74   155.8 1956.23   172.7 1960.45   193.8 1961.48   210.7 1963.69
   219.4 1963.78   240.1    1966   260.6 1968.96   274.8    1972   322.9 1985.78
   335.3 1990.78   379.1 1999.24   385.6 2002.96   392.2 2005.78   424.7 2016.02
#Mann= 3 ,-1,0
       0      .1       0   143.1    .045       0   155.8      .1       0
Bank Sta=143.1,155.8
XS Rating Curve= 0 ,0
Exp/Cntr(USF)=0,0
Exp/Cntr=0.3,0.1

Type RM Length L Ch R = 1 ,287     ,86.3,86.3,85.9
XS GIS Cut Line= 4
2186652.78839214633812.632145451 2186572.1387912633912.258123086
2186601.78937978634049.8368541052186798.66928796634219.438220792
#Sta/Elev= 30
       0 2001.77    21.3  1997.8      47 1991.03    60.6 1989.81      83 1985.06
      90 1981.97    98.5 1976.63   115.4 1962.45   124.2 1956.14   133.2 1952.31
   153.7 1950.05     166 1951.72   182.3 1950.61   190.5 1953.85   198.7 1953.51
   206.9 1951.36     215 1952.18  221.141951.182  233.131951.161   251.9 1953.97
   260.3  1954.2   298.5 1958.46   346.7 1965.45   372.4 1970.22   414.8 1980.87
   431.8 1986.27     441  1988.1   462.1 1995.46   504.4  2006.5   528.8 2013.87
#Mann= 3 ,-1,0
       0      .1       0  221.14    .045       0  233.13      .1       0
#XS Ineff= 2 , 0
          196.68 1960.98
Permanent Ineff=
       F       F
Bank Sta=221.14,233.13
XS Rating Curve= 0 ,0
Exp/Cntr(USF)=0,0
Exp/Cntr=0.3,0.1

Type RM Length L Ch R = 1 ,201     ,58.3,59.6,62.2
XS GIS Cut Line= 6
2186601.79672242633823.4163008522186537.15843931633876.194348528
2186526.48422742 633898.728795852186500.39170947633979.971408565
2186527.67025096634095.0156922642186709.13185308  634234.3734586
#Sta/Elev= 30
       0 1992.52    12.4 1988.95    33.7 1984.77    79.6 1972.15      89 1966.74
   104.4 1954.91     111 1950.56   115.2 1948.85   127.8 1948.81   136.2 1947.36
   148.8 1946.42   157.2 1948.71   178.2 1951.53   194.5 1949.81   203.2 1950.56
   214.5 1950.27     232 1948.41   258.41947.829     2701947.745   277.2 1947.62
   285.4 1948.89   311.9 1950.22   347.9  1955.1   361.5 1954.87   388.2 1957.98
   410.8 1961.64   442.2 1969.87   459.3 1975.57   524.4 1994.08   540.7 1999.76
#Mann= 3 ,-1,0
       0      .1       0   258.4    .045       0     270      .1       0
#XS Ineff= 2 , 0
          181.95 1959.45  284.15         1957.73
Permanent Ineff=
       F       F
Bank Sta=258.4,270
XS Rating Curve= 0 ,0
Exp/Cntr(USF)=0,0
Exp/Cntr=0.3,0.1

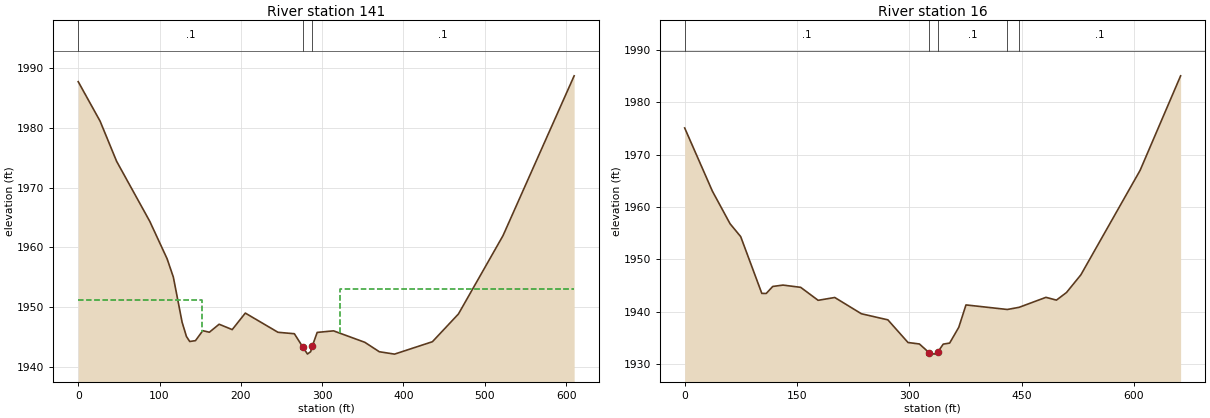
Type RM Length L Ch R = 1 ,141     ,121.7,124.8,119.8
XS GIS Cut Line= 5
2186573.28057197633820.8221811482186472.86391198633899.890417367
2186446.77139402 634159.761353742186492.08954466634183.374446239
2186640.81802374634265.251558896
#Sta/Elev= 30
       0 1987.76    26.9 1981.15    47.2 1974.42      88 1964.35   109.3 1958.08
     117    1955   127.8 1947.42   133.1 1945.05   137.1 1944.21   144.2 1944.35
   153.2 1946.02   161.3 1945.76   173.3  1947.1   189.4  1946.2   205.5 1948.97
   245.7 1945.75   265.8 1945.51     276 1943.33   281.9 1942.11   285.9  1942.5
  287.78  1943.4   293.9 1945.73     314 1945.99   352.5 1944.07   370.3 1942.49
     389 1942.09   435.6 1944.17   467.6 1948.82   522.4 1961.95   609.9 1988.74
#Mann= 3 ,-1,0
       0      .1       0     276    .045       0  287.78      .1       0
#XS Ineff= 2 , 0
          151.62 1951.12  322.45         1953.02
Permanent Ineff=
       F       F
Bank Sta=276,287.78
XS Rating Curve= 0 ,0
Exp/Cntr(USF)=0,0
Exp/Cntr=0.3,0.1

Type RM Length L Ch R = 1 ,16      ,,,
XS GIS Cut Line= 5
2186510.71984178 633809.753568622186418.64448359633957.350169927
2186351.69077358634095.4449604952186353.72289437634121.756209922
2186618.64597251634279.609032789
#Sta/Elev= 30
       0 1975.11      37 1963.04    60.6 1956.81    74.8 1954.35     103  1943.5
   108.9 1943.49   117.6 1944.83   131.3 1945.09   154.9 1944.66   178.2 1942.18
   200.4 1942.72     236 1939.61   271.3 1938.45   298.2 1934.12   313.4 1933.84
   326.3 1932.19   333.2  1931.9  337.871932.269   345.2 1933.81   353.8 1934.01
     366 1937.03   375.6  1941.3   430.8 1940.43   446.5 1940.84   482.4 1942.75
   496.4 1942.22   509.8 1943.67     529 1947.05   608.1 1967.01   662.2 1985.07
#Mann= 5 ,-1,0
       0      .1       0   326.3    .045       0  337.87      .1       0
   430.8     .06       0   446.5      .1       0
Bank Sta=326.3,337.87
XS Rating Curve= 0 ,0
Exp/Cntr(USF)=0,0
Exp/Cntr=0.3,0.1
LCMann Table=0

Chan Stop Cuts=-1
Use User Specified Reach Order=0
Composite Channel Slope=5